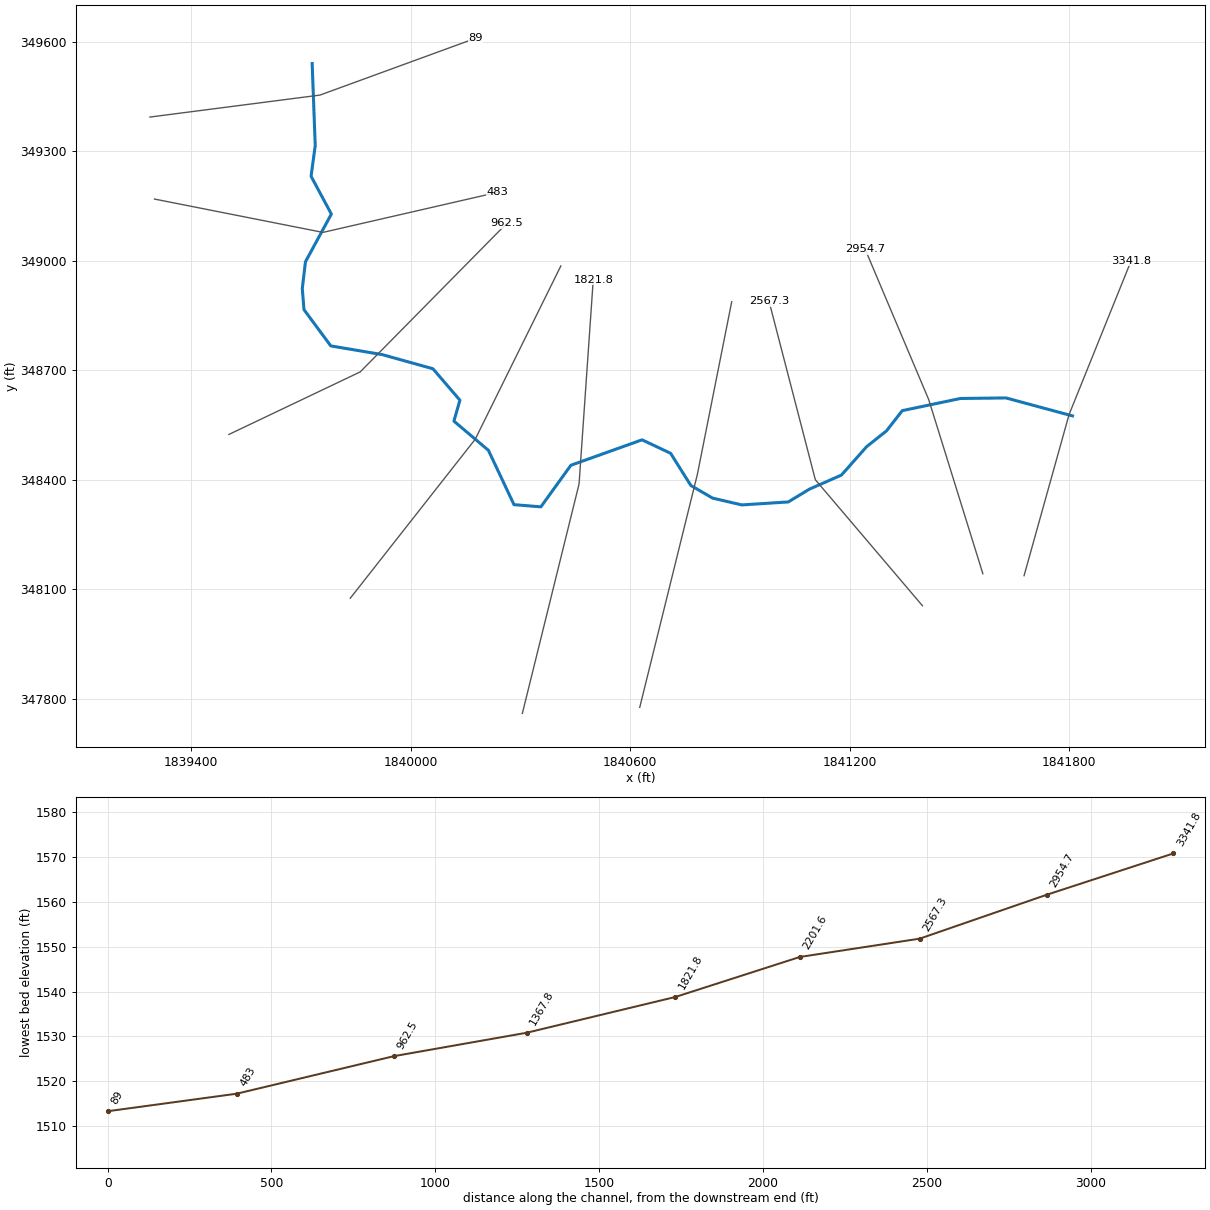
--- MplRn.prj (project) ---

Proj Title=MplRn
Current Plan=p01
Default Exp/Contr=0,0
English Units
Geom File=g01
Flow File=f01
Plan File=p01
BEGIN DESCRIPTION:
END DESCRIPTION:
DSS Export Rating Curves= 0
DSS Export Rating Curve Sorted= 0
DSS Export Volume Flow Curves= 0
DXF OffsetX= 0
DXF OffsetY= 0
DXF ScaleX= 0
DXF ScaleY= 0

--- MplRn.p01 (plan) ---

Plan Title=Floodplain
Program Version=4.00
Geom File=g01
Flow File=f01
K Sum by GR=0
Std Step Tol=0.01
Critical Tol=0.01
Num of Std Step Trials=20
Max Error Tol=0.3
Flow Tol Ratio=0.001
Split Flow NTrial=30
Split Flow Tol=0.02
Split Flow Ratio=0.02
Log Output Level=0
Friction Slope Method=1
Unsteady Friction Slope Method=2
Unsteady Bridges Friction Slope Method=1
Global Log Level=0
CheckData=False
Run HTab=0
Run UNet=0
Run PostProcess=0
UNET Theta=0
UNET Theta Warmup=0
UNET ZTol=0
UNET ZSATol=0
UNET MxIter=0
UNET MaxInSteps=0
UNET DtIC=0
UNET DtMin=0
UNET MaxCRTS=0
UNET WFStab=0
UNET SFStab=0
UNET WFX=0
UNET SFX=0
UNET DSS MLevel=0
UNET DZMax Abort=0
UNET Convert EG Bridges=0
UNET Use Existing IB Tables=0
UNET Froude Limit=0
UNET Froude Power=0
Write IC File=0
Echo Input=False
Echo Output=False
Write Detailed=0

--- MplRn.f01 (steady flow) ---

Flow Title=NFF Regression Equation
Program Version=4.00
Number of Profiles= 1
Profile Names=P100yr
River Rch & RM=MplRn,Main            ,3341.8
843.7612
River Rch & RM=MplRn,Main            ,2954.7
929.4883
River Rch & RM=MplRn,Main            ,89
933.0921
Boundary for River Rch & Prof#=MplRn,Main            , 1
Up Type= 0
Dn Type= 3
Dn Slope=0.014912
DSS Import GetInterval= 0
DSS Import GetPeak= 0
DSS Import FillOption= 0

--- MplRn.g01 (geometry) ---

Geom Title=USGS 3m DEM
Program Version=4.00

River Reach=MplRn     ,Main
Reach XY= 30
     1841809.440      348574.641     1841627.557      348623.852
     1841503.077      348622.352     1841344.035      348588.993
     1841300.980      348533.636     1841246.617      348490.373
     1841177.628      348412.385     1841089.806      348373.718
     1841032.399      348338.864     1840905.284      348330.663
     1840825.184      348349.395     1840765.868      348383.969
     1840710.511      348472.129     1840632.602      348509.034
     1840437.829      348439.325     1840355.758      348325.399
     1840282.270      348331.398     1840212.303      348480.330
     1840117.992      348560.289     1840134.394      348617.696
     1840060.586      348703.806     1839921.169      348742.761
     1839781.350      348766.329     1839707.944      348865.775
     1839703.362      348923.804     1839712.045      348996.991
     1839782.849      349127.772     1839727.358      349231.255
     1839738.747      349315.312     1839730.358      349540.207

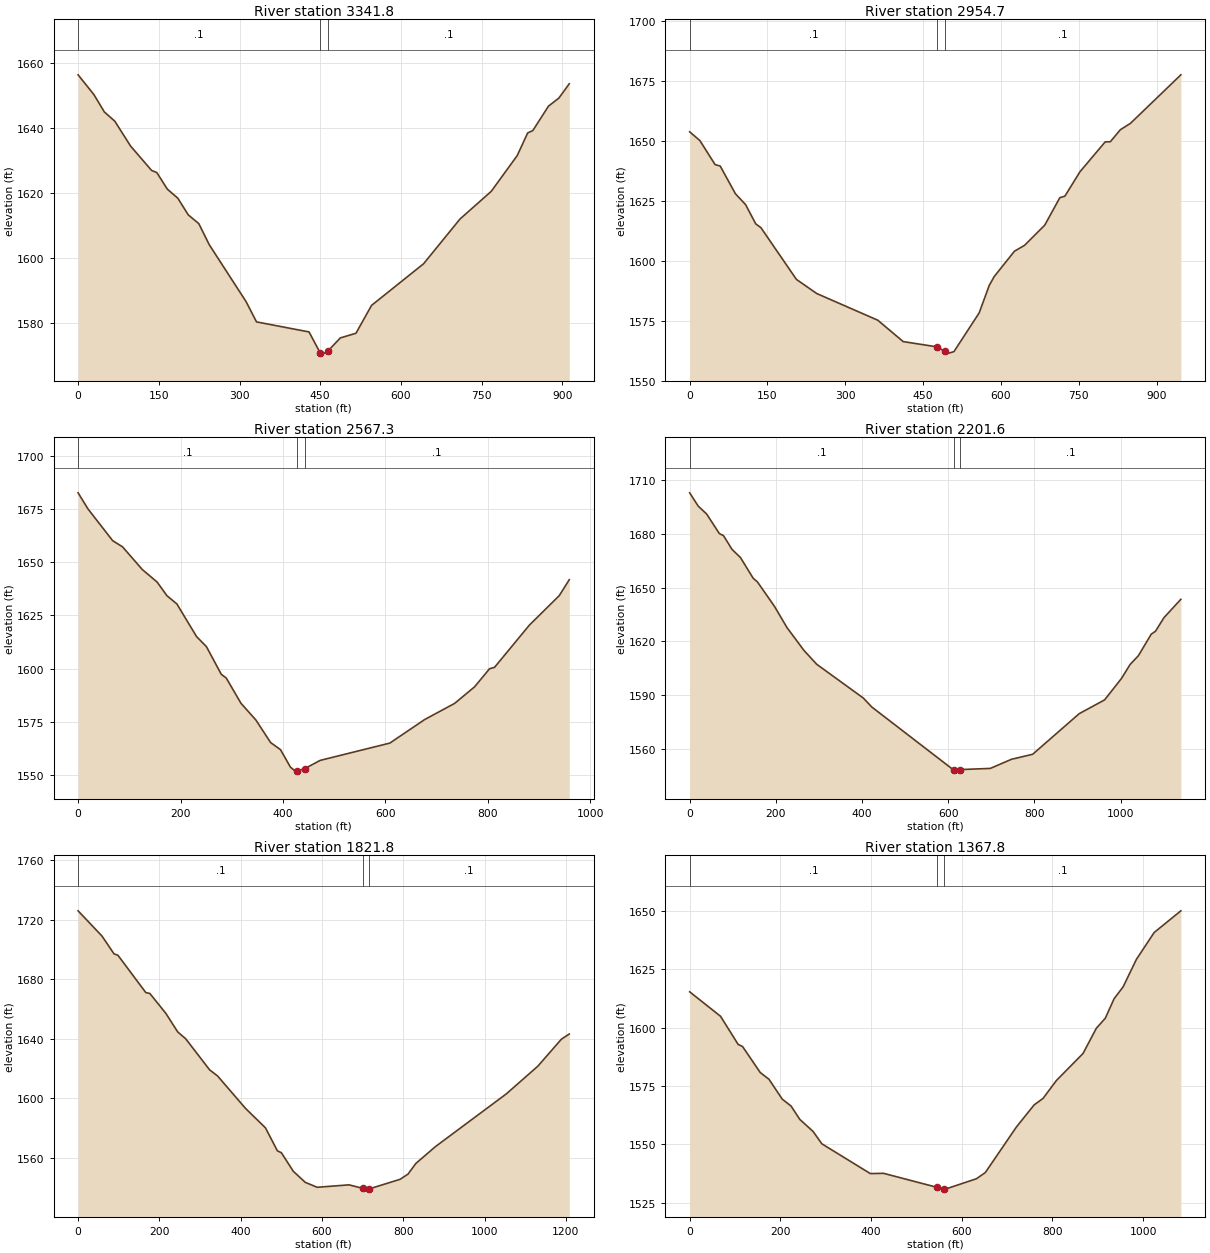
Type RM Length L Ch R = 1 ,3341.8,374.15,387.097,403.178
XS GIS Cut Line= 3
     1841677.093      348136.778     1841800.164      348578.377
     1841969.931      348999.868
#Sta/Elev= 30
       0 1656.43    29.3 1650.37    48.8 1645.01    68.3 1642.15    97.5 1634.52
   136.6 1627.01   146.3 1626.36   165.8 1621.27   185.3 1618.48   204.8 1613.33
   224.3 1610.66   243.8 1604.15   312.1 1586.68   331.6 1580.42   429.2 1577.33
   449.7 1570.95   458.4 1570.81   464.7 1571.54   487.4 1575.49   516.4 1576.92
   545.4 1585.50   642.1 1598.31   709.8 1612.08   767.8 1620.58   816.1 1631.59
   835.5 1638.55   845.1 1639.28   874.2 1646.80   893.5 1649.28   912.8 1653.68
#Mann= 3 , 0 , 0
       0     0.1       0   449.7   0.045       0   464.7     0.1       0
Bank Sta=   449.7,   464.7
Exp/Cntr=0.3,0.1

Type RM Length L Ch R = 1 ,2954.7,377.653,387.408,393.948
XS GIS Cut Line= 3
     1841564.433      348142.139     1841416.278      348619.470
     1841242.492      349031.407
#Sta/Elev= 30
       0 1653.72    19.6 1650.10    49.0 1640.07    58.8 1639.49    88.2 1627.93
   107.8 1623.41   127.4 1615.38   137.2 1613.85   205.8 1592.27   245.0 1586.39
   362.6 1575.29   411.6 1566.38   477.2 1564.18   492.2 1562.27   499.8 1561.58
   509.5 1562.22   558.1 1578.34   577.6 1589.83   587.3 1593.52   626.1 1604.01
   645.6 1606.46   684.5 1614.86   713.6 1626.30   723.3 1626.93   752.5 1637.13
   801.1 1649.55   810.8 1649.56   830.3 1654.60   849.7 1657.24   946.9 1677.45
#Mann= 3 , 0 , 0
       0     0.1       0   477.2   0.045       0   492.2     0.1       0
Bank Sta=   477.2,   492.2
Exp/Cntr=0.3,0.1

Type RM Length L Ch R = 1 ,2567.3,387.242,365.654,347.09
XS GIS Cut Line= 3
     1841399.352      348054.262     1841106.291      348399.713
     1840979.465      348889.449
#Sta/Elev= 30
       0 1682.64    19.3 1675.07    67.5 1660.14    86.7 1657.27   125.3 1646.59
   154.2 1640.72   173.5 1634.26   192.8 1630.42   231.3 1615.06   250.6 1610.31
   279.5 1597.33   289.2 1595.59   318.1 1583.66   347.0 1575.87   375.9 1565.22
   395.2 1561.89   414.5 1553.68   424.1 1551.80   427.6 1551.92   442.6 1552.98
   472.5 1556.84   608.7 1564.99   676.8 1576.08   735.1 1583.64   774.1 1591.44
   803.2 1599.92   813.0 1600.60   881.1 1620.46   939.4 1634.32   958.9 1641.80
#Mann= 3 , 0 , 0
       0     0.1       0   427.6   0.045       0   442.6     0.1       0
Bank Sta=   427.6,   442.6
Exp/Cntr=0.3,0.1

Type RM Length L Ch R = 1 ,2201.6,375.336,379.809,383.719
XS GIS Cut Line= 3
     1840626.101      347775.792     1840783.865      348415.007
     1840877.630      348887.431
#Sta/Elev= 30
       0 1702.83    19.7 1695.46    39.3 1691.04    68.8 1680.14    78.6 1678.93
    98.3 1671.30   117.9 1666.74   147.4 1655.21   157.2 1653.20   196.5 1639.66
   226.0 1627.67   265.3 1614.98   294.8 1607.29   402.9 1588.47   422.6 1583.47
   613.5 1548.19   619.1 1547.72   628.5 1548.59   697.7 1549.23   746.9 1554.32
   796.0 1557.10   904.1 1579.75   963.1 1587.44  1002.4 1599.44  1022.1 1607.12
  1041.7 1612.14  1071.2 1624.04  1081.1 1625.67  1100.7 1633.22  1140.0 1643.50
#Mann= 3 , 0 , 0
       0     0.1       0   613.5   0.045       0   628.5     0.1       0
Bank Sta=   613.5,   628.5
Exp/Cntr=0.3,0.1

Type RM Length L Ch R = 1 ,1821.8,469.565,454.005,442.229
XS GIS Cut Line= 3
     1840305.133      347759.471     1840460.177      348387.806
     1840498.991      348947.678
#Sta/Elev= 30
       0 1726.10    58.8 1709.12    88.3 1697.18    98.1 1696.17   166.7 1671.05
   176.5 1670.49   215.7 1657.18   245.1 1644.60   264.8 1639.97   323.6 1619.07
   343.2 1614.95   411.8 1593.16   460.9 1580.07   490.3 1564.58   500.1 1563.31
   529.5 1550.79   558.9 1543.36   588.3 1540.04   666.5 1541.68     700 1539.35
   705.2 1538.80     715 1538.85   792.3 1545.42   811.7 1548.91   831.0 1556.10
   879.4 1567.47  1053.6 1602.91  1131.0 1621.51  1189.0 1639.72  1208.4 1643.19
#Mann= 3 , 0 , 0
       0     0.1       0     700   0.045       0     715     0.1       0
Bank Sta=     700,     715
Exp/Cntr=0.3,0.1

Type RM Length L Ch R = 1 ,1367.8,409.483,405.287,394.957
XS GIS Cut Line= 3
     1839834.562      348074.999     1840176.335      348510.825
     1840410.383      348985.584
#Sta/Elev= 30
       0 1615.32    68.0 1604.85   106.9 1592.79   116.6 1591.90   155.5 1580.78
   174.9 1577.86   204.1 1569.37   223.5 1566.41   242.9 1560.67   272.1 1555.53
   291.5 1550.23   398.4 1537.47   427.5 1537.59   546.4 1531.54   561.4 1530.87
   563.7 1530.82   632.3 1535.26   651.9 1537.90   720.5 1557.42   759.7 1566.91
   779.3 1569.68   808.7 1577.33   867.5 1588.92   896.9 1599.75   916.5 1603.99
   936.1 1612.42   955.7 1617.39   985.1 1629.20  1024.4 1640.74  1083.2 1650.01
#Mann= 3 , 0 , 0
       0     0.1       0   546.4   0.045       0   561.4     0.1       0
Bank Sta=   546.4,   561.4
Exp/Cntr=0.3,0.1

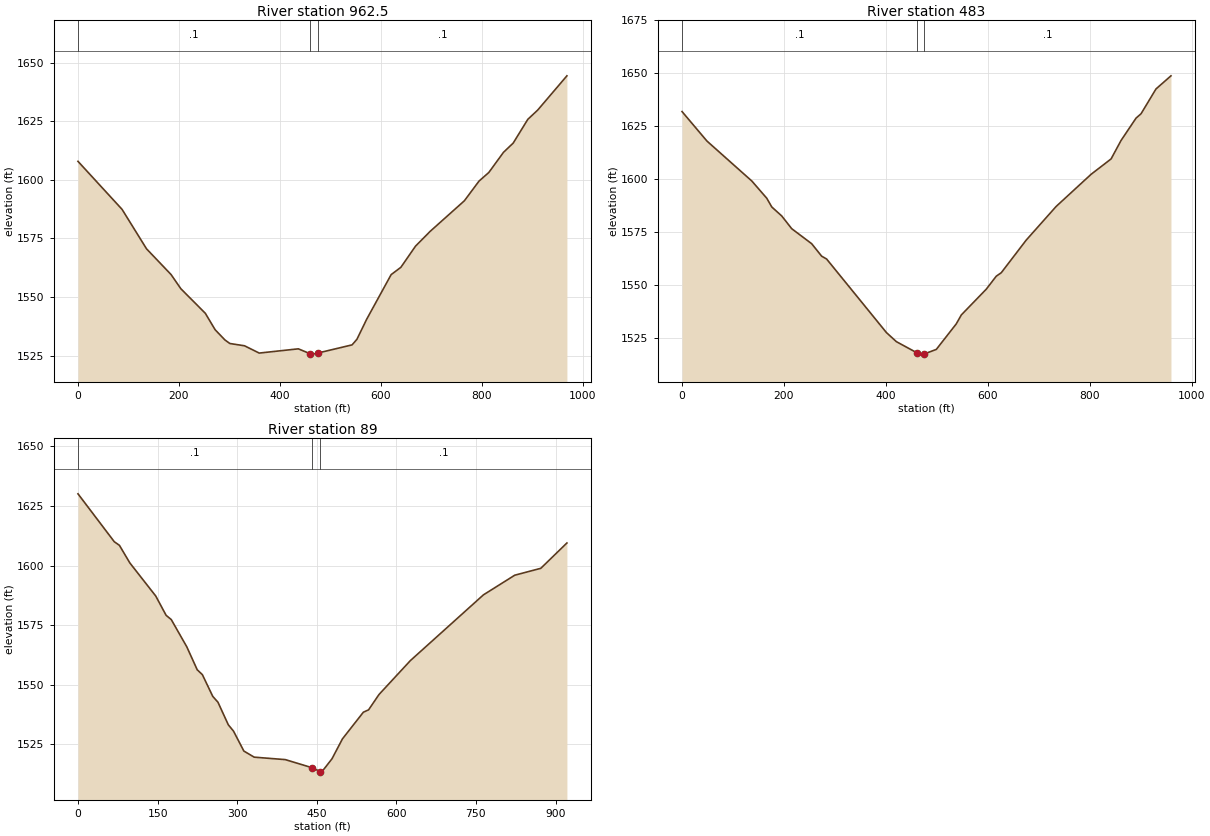
Type RM Length L Ch R = 1 ,962.5,501.062,479.51,469.237
XS GIS Cut Line= 3
     1839502.715      348523.809     1839861.763      348695.173
     1840262.198      349101.947
#Sta/Elev= 30
       0 1607.89    87.3 1587.40   135.8 1570.55   184.4 1559.57   203.8 1553.51
   252.3 1543.02   271.7 1536.01   291.1 1531.65   300.8 1530.14   329.9 1529.16
   359.0 1526.05   436.5 1527.86   459.7 1525.79   465.6 1525.60   474.7 1526.04
   543.0 1529.55   552.6 1531.93   572.0 1540.52   620.4 1559.54   639.7 1562.67
   668.7 1571.70   697.8 1578.03   765.5 1591.07   794.5 1599.47   813.9 1603.14
   842.9 1611.73   862.2 1615.69   891.2 1625.84   910.6 1629.75   968.6 1644.40
#Mann= 3 , 0 , 0
       0     0.1       0   459.7   0.045       0   474.7     0.1       0
Bank Sta=   459.7,   474.7
Exp/Cntr=0.3,0.1

Type RM Length L Ch R = 1 ,483,385.555,394.01,391.434
XS GIS Cut Line= 3
     1839299.194      349168.812     1839759.834      349077.428
     1840237.186      349187.242
#Sta/Elev= 30
       0 1631.89    48.9 1617.95   137.0 1599.05   166.3 1590.91   176.1 1586.79
   195.7 1582.53   215.2 1576.53   254.4 1569.42   273.9 1563.55   283.7 1562.19
   401.1 1527.41   420.7 1523.11   460.7 1517.88   469.6 1517.23   475.7 1517.35
   499.0 1519.47   538.2 1531.56   548.0 1535.75   597.0 1547.94   616.6 1554.07
   626.4 1555.71   675.3 1571.11   734.1 1587.04   802.7 1602.24   841.9 1609.51
   861.5 1618.25   890.9 1628.80   900.7 1630.86   930.0 1642.58   959.4 1648.79
#Mann= 3 , 0 , 0
       0     0.1       0   460.7   0.045       0   475.7     0.1       0
Bank Sta=   460.7,   475.7
Exp/Cntr=0.3,0.1

Type RM Length L Ch R = 1 ,89,91.406,89.016,85.894
XS GIS Cut Line= 3
     1839286.713      349393.491     1839751.720      349453.716
     1840176.719      349609.203
#Sta/Elev= 30
       0 1630.11    68.4 1610.01    78.1 1608.49    97.7 1601.12   146.5 1587.24
   166.1 1579.12   175.8 1577.34   205.1 1565.89   224.7 1556.27   234.4 1554.23
   254.0 1545.11   263.8 1542.65   283.3 1533.18   293.1 1530.53   312.6 1522.16
   332.1 1519.60   390.7 1518.57   441.9 1515.12   456.9 1513.51   459.1 1513.32
   478.7 1518.92   498.4 1527.28   537.8 1538.47   547.6 1539.45   567.3 1545.90
   626.3 1560.10   764.0 1587.70   823.1 1595.96   872.2 1598.85   921.4 1609.48
#Mann= 3 , 0 , 0
       0     0.1       0   441.9   0.045       0   456.9     0.1       0
Bank Sta=   441.9,   456.9
Exp/Cntr=0.3,0.1